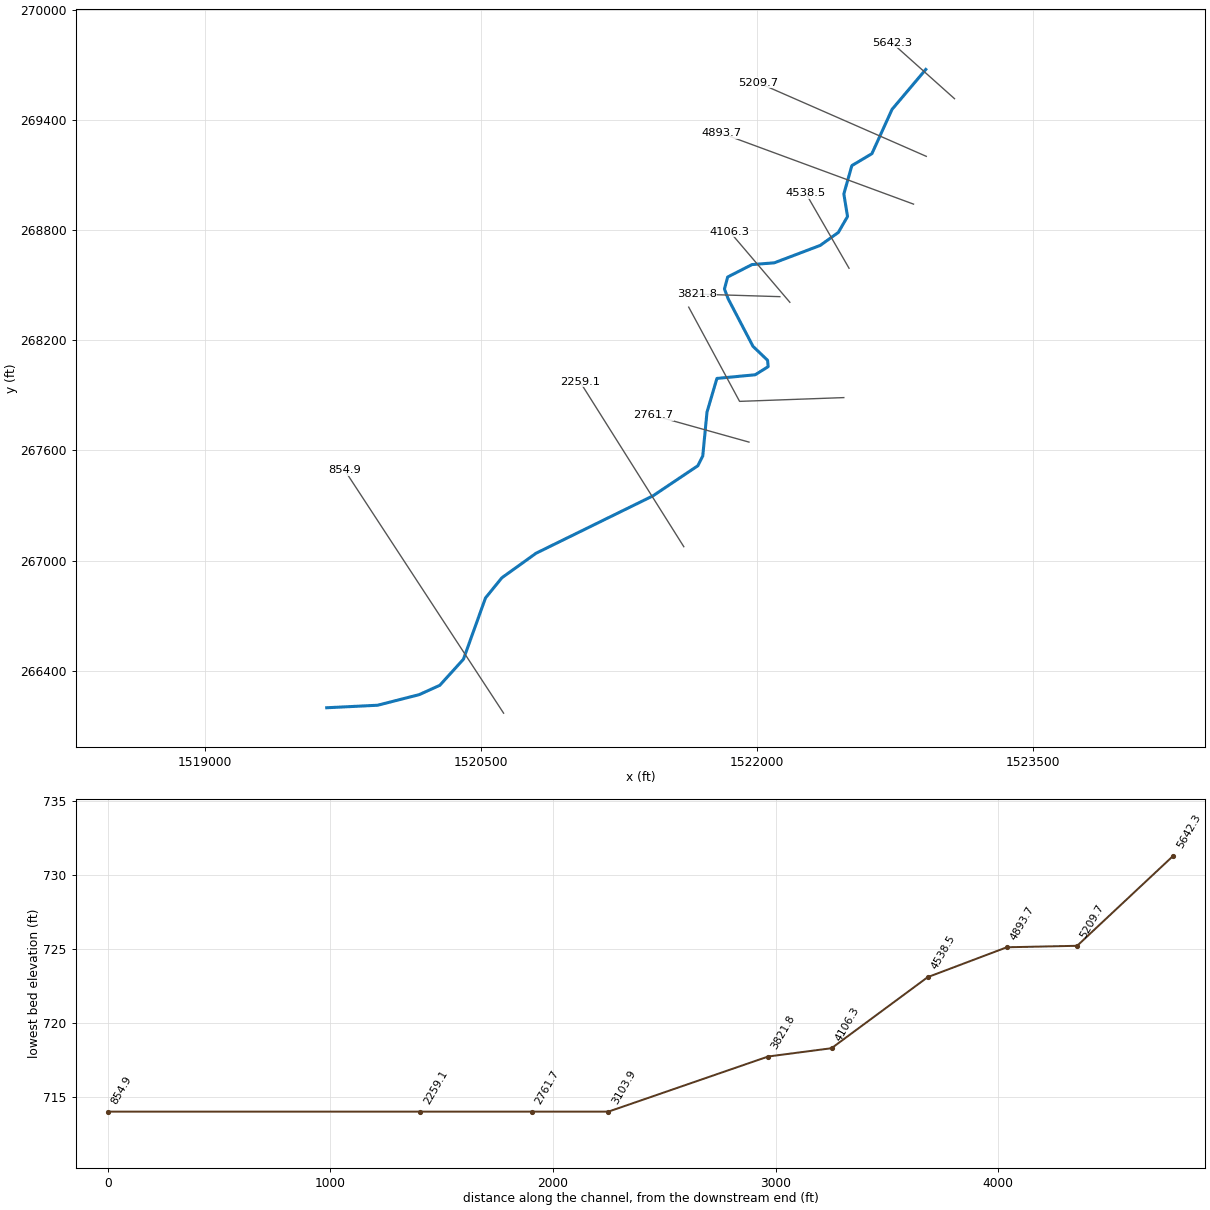
--- LSTRN.prj (project) ---

Proj Title=LSTRN
Current Plan=p01
Default Exp/Contr=0,0
English Units
Geom File=g01
Flow File=f01
Plan File=p01
BEGIN DESCRIPTION:
END DESCRIPTION:
DSS Export Rating Curves= 0
DSS Export Rating Curve Sorted= 0
DSS Export Volume Flow Curves= 0
DXF OffsetX= 0
DXF OffsetY= 0
DXF ScaleX= 0
DXF ScaleY= 0

--- LSTRN.p01 (plan) ---

Plan Title=Floodplain
Program Version=4.00
Geom File=g01
Flow File=f01
K Sum by GR=0
Std Step Tol=0.01
Critical Tol=0.01
Num of Std Step Trials=20
Max Error Tol=0.3
Flow Tol Ratio=0.001
Split Flow NTrial=30
Split Flow Tol=0.02
Split Flow Ratio=0.02
Log Output Level=0
Friction Slope Method=1
Unsteady Friction Slope Method=2
Unsteady Bridges Friction Slope Method=1
Global Log Level=0
CheckData=False
Run HTab=0
Run UNet=0
Run PostProcess=0
UNET Theta=0
UNET Theta Warmup=0
UNET ZTol=0
UNET ZSATol=0
UNET MxIter=0
UNET MaxInSteps=0
UNET DtIC=0
UNET DtMin=0
UNET MaxCRTS=0
UNET WFStab=0
UNET SFStab=0
UNET WFX=0
UNET SFX=0
UNET DSS MLevel=0
UNET DZMax Abort=0
UNET Convert EG Bridges=0
UNET Use Existing IB Tables=0
UNET Froude Limit=0
UNET Froude Power=0
Write IC File=0
Echo Input=False
Echo Output=False
Write Detailed=0

--- LSTRN.f01 (steady flow) ---

Flow Title=NFF Regression Equation
Program Version=4.10
Number of Profiles= 1
Profile Names=P100yr
River Rch & RM=LSTRN,Main            ,5642.3
894.4316
River Rch & RM=LSTRN,Main            ,5209.7
897.2502
River Rch & RM=LSTRN,Main            ,4893.7
1072.641
River Rch & RM=LSTRN,Main            ,854.9
1184.354
Boundary for River Rch & Prof#=LSTRN,Main            , 1
Up Type= 0
Dn Type= 3
Dn Slope=0.001
DSS Import GetInterval= 0
DSS Import GetPeak= 0
DSS Import FillOption= 0

--- LSTRN.g01 (geometry) ---

Geom Title=USGS 10m DEM
Program Version=4.10

River Reach=LSTRN           ,Main
Reach XY= 30
     1522915.921      269674.258     1522732.558      269456.697
     1522622.938      269215.509     1522514.116       269150.57
     1522470.577      268996.383     1522490.651       268873.53
      1522440.54      268786.655     1522342.173      268716.198
     1522092.747      268621.421     1521971.621      268611.905
     1521839.329      268544.196     1521821.809      268478.737
     1521842.339      268424.635     1521977.003      268166.592
     1522055.996      268091.071     1522059.468      268056.349
     1521989.156      268012.078     1521780.822      267992.113
     1521726.922      267808.506     1521703.923      267570.036
     1521677.291      267516.774     1521433.031      267352.763
     1520797.615      267040.263     1520611.851      266906.583
     1520523.309      266797.208     1520403.517      266463.874
     1520275.045      266321.513     1520163.006       266270.75
     1519937.374      266213.088     1519660.247      266199.337

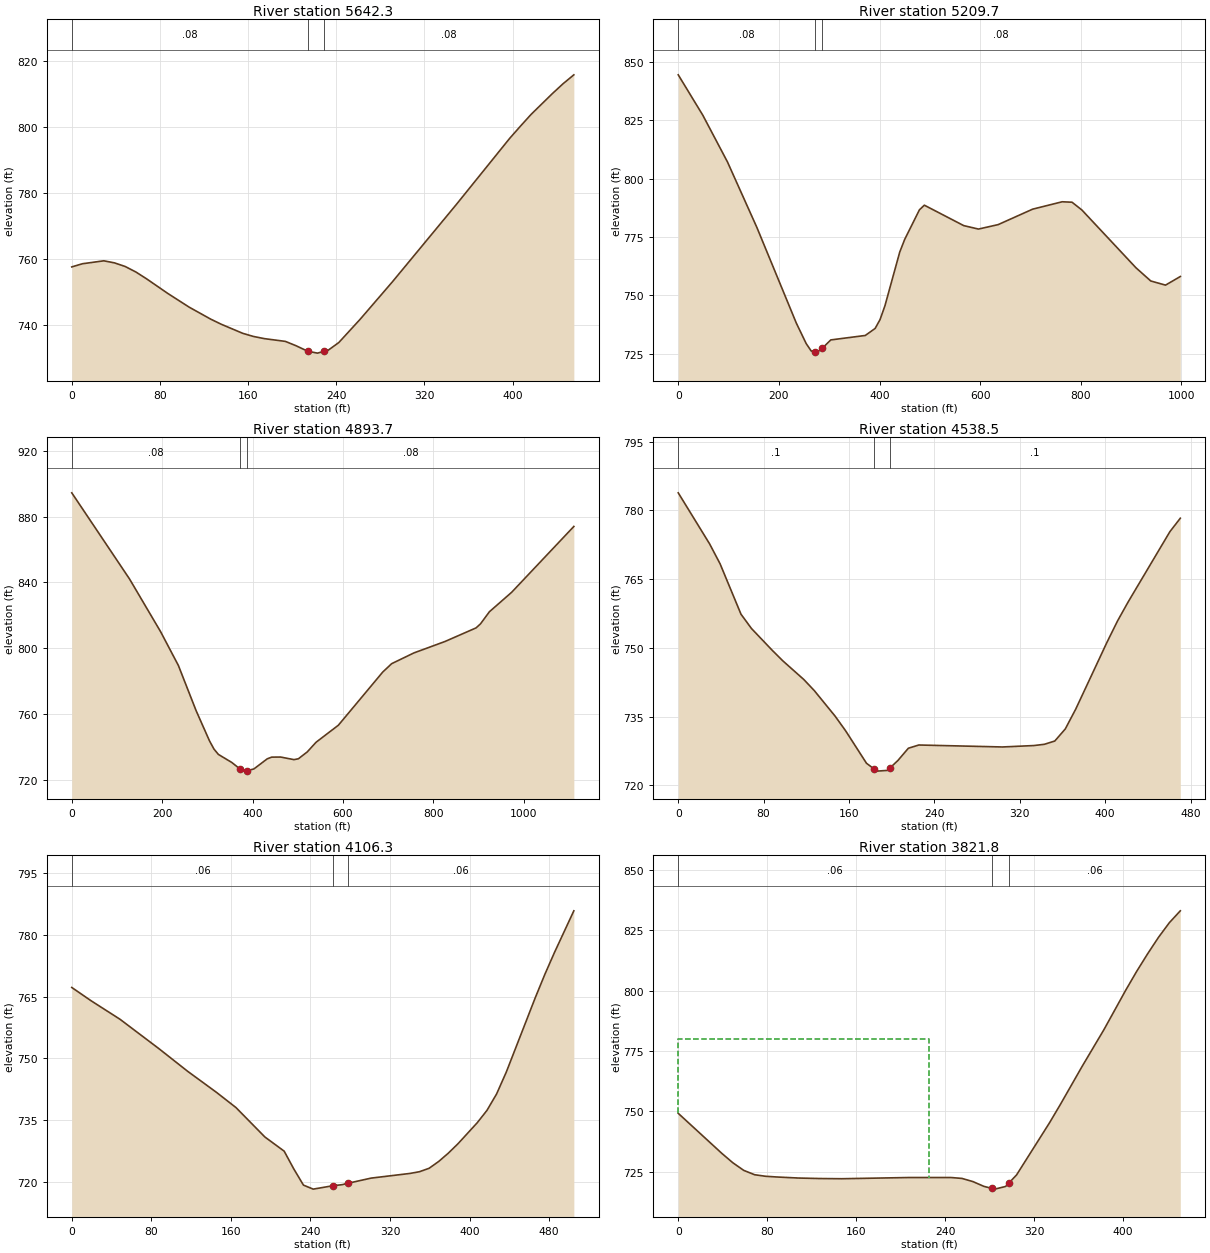
Type RM Length L Ch R = 1 ,5642.3  ,424.6,432.6,439
XS GIS Cut Line= 2
     1523072.038      269514.906     1522732.548      269818.657
#Sta/Elev= 30
       0  757.48     9.7  758.44    29.1  759.33    38.8   758.7    48.5   757.6
    58.2  755.93    67.8  753.88    87.2  749.41   106.6  745.25     126  741.64
   135.7  740.07   155.1  737.33   164.8  736.38   174.5  735.73   193.8  734.88
   203.5  733.56   214.1  731.89   222.9  731.32   229.1  731.88   232.6  732.19
   242.3  734.54   261.7  741.62   290.8  752.92   348.9  776.42   397.4  796.53
   407.1   800.2   416.8  803.78   436.2  810.12   445.8  813.08   455.5  815.76
#Mann= 3 , 0 , 0
       0     .08       0   214.1    .045       0   229.1     .08       0
Bank Sta=214.1,229.1
XS Rating Curve= 0 ,0
Exp/Cntr=0.3,0.1

Type RM Length L Ch R = 1 ,5209.7  ,314.6,316,317.2
XS GIS Cut Line= 2
       1522918.6      269201.098     1522004.906      269601.965
#Sta/Elev= 30
       0  844.52    48.9  827.19    97.8   807.2   156.5     779   234.8  738.03
   254.3  729.31   264.1  726.19     271  725.51   273.9  725.22     286  727.26
   303.2  730.88   371.7  732.79   391.3  735.79   401.1  739.62   410.8  745.52
   440.2  768.53     450  773.95   479.3  786.63   489.1  788.64   567.4  779.88
   596.7   778.4   635.8  780.31   704.3  786.93     763   790.1   782.6  789.91
   802.1   786.6   909.7   761.8   939.1  756.15   968.4  754.37   997.8  758.06
#Mann= 3 , 0 , 0
       0     .08       0     271    .045       0     286     .08       0
Bank Sta=271,286
XS Rating Curve= 0 ,0
Exp/Cntr=0.3,0.1

Type RM Length L Ch R = 1 ,4893.7  ,370.7,355.2,339.4
XS GIS Cut Line= 2
     1522849.341      268940.949     1521806.989      269325.924
#Sta/Elev= 30
       0  894.55   127.8  842.12   196.7  809.98     236  789.42   275.3  761.87
   304.8  743.56   314.7  738.56   324.5  735.29     354  730.42   372.6  726.39
   383.5  725.12   387.6  725.29   403.2  726.48   432.7  732.62   442.5  733.64
   462.2  733.69   491.7  732.12   501.5  732.63   521.2  736.82   540.8  742.73
     590  753.05   688.3  785.45     708  790.54   757.2  797.08     826  804.04
   894.8  812.32   904.7   814.8   924.3  822.14   973.5  833.98  1111.2  874.08
#Mann= 3 , 0 , 0
       0     .08       0   372.6    .045       0   387.6     .08       0
Bank Sta=372.6,387.6
XS Rating Curve= 0 ,0
Exp/Cntr=0.3,0.1

Type RM Length L Ch R = 1 ,4538.5  ,425.9,432.2,439
XS GIS Cut Line= 2
     1522498.838      268591.941      1522264.13       268999.58
#Sta/Elev= 30
       0  783.82    29.4  772.68    39.2  768.34    58.8  757.34    68.6  754.22
    88.2  749.43      98  747.16   117.6   743.1   127.4  740.69     147  735.09
   156.8  731.91   176.4  724.81     183  723.66   186.2   723.1     196  723.26
     198   723.7   205.8  725.42   215.6  728.09   225.4   728.8   303.8  728.37
   333.2  728.68     343  728.95   352.8  729.67   362.6  732.29   372.4  736.62
   401.8  751.26   411.6  755.87   421.4  759.96   460.6  775.33   470.4  778.28
#Mann= 3 , 0 , 0
       0      .1       0     183    .045       0     198      .1       0
Bank Sta=183,198
XS Rating Curve= 0 ,0
Exp/Cntr=0.3,0.1

Type RM Length L Ch R = 1 ,4106.3  ,272.1,284.5,300.2
XS GIS Cut Line= 2
     1522177.246      268406.587      1521850.18      268791.278
#Sta/Elev= 30
       0  767.21    19.4  763.99    48.6  759.48    87.4  752.41   116.5  746.88
   145.6  741.75   165.1  738.08   194.2  730.94   213.6   727.5   223.3  723.18
     233  719.26   242.8  718.29   262.7  719.12   271.9  719.37   277.7  719.71
     301  720.96   339.9  722.09   349.6  722.51   359.3  723.34     369     725
   378.7  727.02   388.4   729.3   407.8  734.41   417.5  737.38   427.2  741.37
     437   746.7   466.1  764.72   475.8  770.42   485.5  775.74   504.9   785.8
#Mann= 3 , 0 , 0
       0     .06       0   262.7    .045       0   277.7     .06       0
Bank Sta=262.7,277.7
XS Rating Curve= 0 ,0
Exp/Cntr=0.3,0.1

Type RM Length L Ch R = 1 ,3821.8  ,765.2,717.9,713.5
XS GIS Cut Line= 2
     1522122.766      268437.242     1521671.377      268451.131
#Sta/Elev= 30
       0  749.16    39.3  732.52    49.1  728.67    58.9  725.51    68.7   723.7
    78.5  723.06    88.4  722.77     108  722.33   127.6  722.12   147.3  722.04
   206.2  722.53   245.4  722.54   255.2  722.17   265.1  720.85   274.9  718.88
   282.1  718.04   284.7  717.73   294.5  718.84   297.1  720.11   304.3  723.61
   333.8  745.12   343.6  752.74   363.2  768.55   382.9  783.85   402.5   800.2
   412.3  807.97   422.2   815.3     432  822.14   441.8  828.23   451.6  833.12
#Mann= 3 , 0 , 0
       0     .06       0   282.1    .045       0   297.1     .06       0
#XS Ineff= 2 , 0
          225.36  779.78
Permanent Ineff=
       F       F
Bank Sta=282.1,297.1
XS Rating Curve= 0 ,0
Exp/Cntr=0.3,0.1

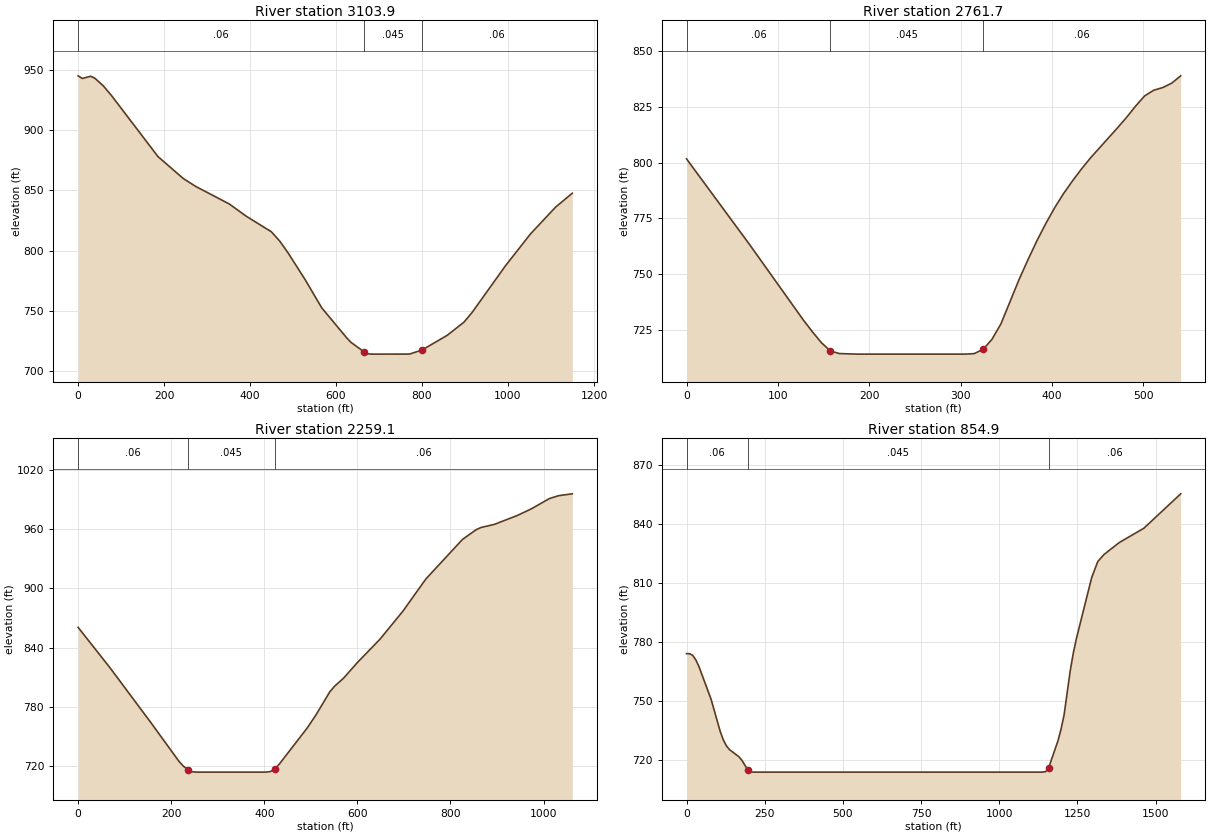
Type RM Length L Ch R = 1 ,3103.9  ,324.1,342.2,359.8
XS GIS Cut Line= 3
     1522470.526      267887.766     1521904.029      267867.186
      1521627.58      268380.129
#Sta/Elev= 30
       0  945.07     9.8  942.86    29.3  944.73    39.1  943.05    58.6  936.74
    78.2  928.44   185.7  878.05   244.3   859.9   273.7   853.2   351.8  838.64
     391  828.54   449.6  815.57   469.1  807.83   488.7   797.9   527.8  776.01
   566.9  752.36   625.1  727.39   634.8  723.78     664  716.18   673.7  714.29
   683.4     714   770.8  714.03     800  717.42   858.2  729.52   897.1  740.36
   916.5  748.58   994.2  787.38  1052.4  813.83  1110.7  836.04  1149.6  847.61
#Mann= 3 , 0 , 0
       0     .06       0     664    .045       0     800     .06       0
Bank Sta=664,800
XS Rating Curve= 0 ,0
Exp/Cntr=0.3,0.1

Type RM Length L Ch R = 1 ,2761.7  ,519.3,502.6,485.9
XS GIS Cut Line= 2
     1521955.059      267645.543     1521434.225      267791.376
#Sta/Elev= 30
       0  801.69    68.8  763.33   127.8  729.36   137.7  724.07   147.5  719.19
   157.3  715.48   167.2  714.25   186.8     714   304.8     714   314.7  714.22
   324.5  716.09   334.4   720.7   344.2  727.64   363.8  747.34   373.7  756.38
   383.5  764.91   393.4  772.78   403.2  779.93     413  786.31   422.9  792.06
   432.7  797.37   442.5  802.29     472  815.76   481.9  820.47   491.7  825.48
   501.5     830   511.4  832.54   521.2  833.72     531   835.7   540.9     839
#Mann= 3 , 0 , 0
       0     .06       0   157.3    .045       0   324.5     .06       0
Bank Sta=157.3,324.5
XS Rating Curve= 0 ,0
Exp/Cntr=0.3,0.1

Type RM Length L Ch R = 1 ,2259.1  ,1405.6,1404.2,1402.4
XS GIS Cut Line= 2
     1521600.892      267076.098     1521035.878      267975.101
#Sta/Elev= 30
       0  860.47    68.8   819.4   157.3  763.48   216.3  725.18   226.1  720.08
     236  716.35   245.8  714.33   255.6     714   403.1     714   412.9  714.52
   422.8  717.14   432.6  722.33   491.6  758.25   511.2  771.98   540.7   795.2
   550.6   800.7   570.2  808.99   599.7  824.69   648.9  848.67     698  876.96
   747.2  909.42   825.8  949.42   855.4  959.33   865.2  961.45   894.7  964.71
   943.8   973.7   973.3  980.25  1012.6  990.78  1032.3   993.7  1061.8  995.58
#Mann= 3 , 0 , 0
       0     .06       0     236    .045       0   422.8     .06       0
Bank Sta=236,422.8
XS Rating Curve= 0 ,0
Exp/Cntr=0.3,0.1

Type RM Length L Ch R = 1 ,854.9   ,864.2,854.9,845.8
XS GIS Cut Line= 2
     1520621.626      266169.908     1519757.668      267493.083
#Sta/Elev= 30
       0  774.21     9.8  774.21    19.6  773.35    29.4  771.14    39.3  767.82
    78.5  751.04     108  734.52   117.8  730.34   127.6  727.35   137.4  725.42
   166.9   721.9   176.7   720.1   196.3  715.03   206.1  714.06   215.9     714
  1138.6     714  1148.4  714.23  1158.2   716.3  1187.6  729.82  1197.5  735.74
  1207.3  742.99  1226.9   765.4  1236.7  774.39  1246.5  781.71  1295.6  812.87
  1315.2  821.06  1334.9  824.59    1384   830.7  1462.5  837.95  1580.3  855.44
#Mann= 3 , 0 , 0
       0     .06       0   196.3    .045       0  1158.2     .06       0
Bank Sta=196.3,1158.2
XS Rating Curve= 0 ,0
Exp/Cntr=0.3,0.1

Chan Stop Cuts=-1
Use User Specified Reach Order=0
Composite Channel Slope=5